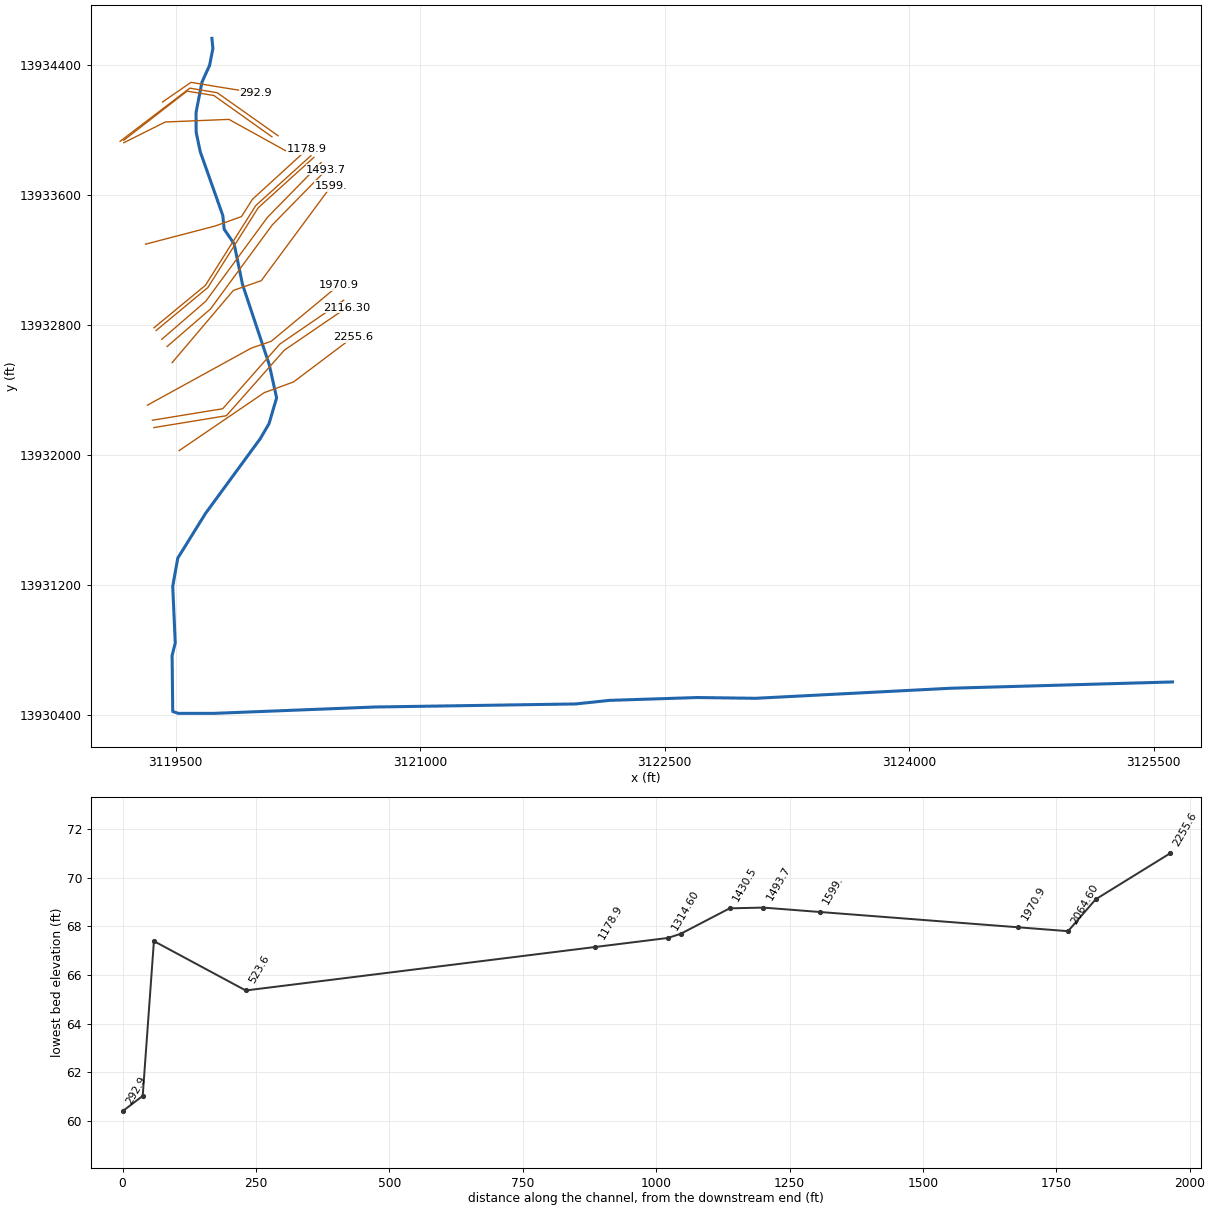
--- K111-03-00.prj (project) ---

Proj Title=K111-03-00
Current Plan=p02
Default Exp/Contr=.3,.1
English Units
Geom File=g01
Flow File=f02
Flow File=f01
Flow File=f04
Plan File=p02
Plan File=p01
Plan File=p04
Y Axis Title=Elevation
X Axis Title(PF)=Main Channel Distance
X Axis Title(XS)=Station
BEGIN DESCRIPTION:
Cypress Creek Watershed
Turkey Creek Tributary
HCFCD Unit K111-03-00
Flood Hazard Model
10, 2, 1, 0.2%
Filename K111-03-00
Prepared by:  Halff Associates  DATE:  March 26, 2004
Reviewed by:  _____________________  DATE:  __________________
STATUS (Final)
END DESCRIPTION:
DSS File=dss
DSS Export Rating Curves= 0
DSS Export Rating Curve Sorted= 0
DSS Export Volume Flow Curves= 0
DXF OffsetX= 0
DXF OffsetY= 0
DXF ScaleX= 1
DXF ScaleY= 10

--- K111-03-00.p02 (plan) ---

Plan Title=Floodway
Version=Version 3.0.1  Mar 2001
Short Identifier=Floodway0607
Geom File=g01
Flow File=f02
Subcritical Flow
K Sum by GR= 0
Std Step Tol= 0.01
Critical Tol= 0.01
Num of Std Step Trials= 20
Max Error Tol= 0.3
Flow Tol Ratio= 0.001
Split Flow NTrial= 30
Split Flow Tol= 0.02
Split Flow Ratio= 0.02
Log Output Level= 0
Friction Slope Method= 1
Unsteady Friction Slope Method= 2
Parabolic Critical Depth
Global Vel Dist= 0 , 0 , 0
Global Log Level= 0
CheckData=True
Encroach Param=-1 ,0,0, 2
Encroach River=K111-03-00
Encroach Reach=Reach - 1
Encroach Node=2255.6
       1  4944.8  5084.8
Encroach Node=2116.30
       1 4285.87 4370.74
Encroach Node=2090.00
       1 4285.87 4370.74
Encroach Node=2064.60
       1 4285.87 4370.74
Encroach Node=1970.9
       1  4933.2  5062.5
Encroach Node=1599.
       1    4935    5065
Encroach Node=1493.7
       13489.2893595.857
Encroach Node=1462.1
       1 3489.29 3595.86
Encroach Node=1430.5
       13489.2893595.857
Encroach Node=1338.60
       1 4909.25 5046.75
Encroach Node=1326.60
       1 4909.25 5046.75
Encroach Node=1314.60
       1 4909.25 5046.75
Encroach Node=1178.9
       1  4938.1  5068.6
Encroach Node=523.6
       1  4957.7  5063.1
Encroach Node=351.6
       1  4959.1    5079
Encroach Node=341.1
       1  4959.1    5079
Encroach Node=330.6
       1    4943    5083
Encroach Node=292.9
       1    4943    5083
Encroach Reach=K111-03-00_0003
Encroach Node=2255.6
       1  4944.8  5084.8
Encroach Node=2116.30
       1 4285.87 4370.74
Encroach Node=2090.00
       1 4285.87 4370.74
Encroach Node=2064.60
       1 4285.87 4370.74
Encroach Node=1970.9
       1  4933.2  5062.5
Encroach Node=1599.
       1    4935    5065
Encroach Node=1493.7
       13489.2893595.857
Encroach Node=1462.1
       1 3489.29 3595.86
Encroach Node=1430.5
       13489.2893595.857
Encroach Node=1338.60
       1 4909.25 5046.75
Encroach Node=1326.60
       1 4909.25 5046.75
Encroach Node=1314.60
       1 4909.25 5046.75
Encroach Node=1178.9
       1  4938.1  5068.6
Encroach Node=523.6
       1  4957.7  5063.1
Encroach Node=351.6
       1  4959.1    5079
Encroach Node=341.1
       1  4959.1    5079
Encroach Node=330.6
       1    4943    5083
Encroach Node=292.9
       1    4943    5083
Computation Interval=1HOUR
Output Interval=1HOUR
Run HTab= 0
Run UNet= 0
Run PostProcess= 0
UNET Theta= 1
UNET ZTol= 0.02
UNET ZSATol= 0.1
UNET MxIter= 20
UNET MaxInSteps= 20
UNET DtIC= 0
UNET DtMin= 0
UNET MaxCRTS= 20
UNET WFStab= 2
UNET SFStab= 1
UNET WFX= 1
UNET SFX= 1
UNET Convert EG Bridges=-1
UNET Use Existing IB Tables=-1
Instantaneous Interval=1HOUR
Write IC File= 0
Write Velocity= 0
Write Detailed= 0

--- K111-03-00.p01 (plan) ---

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Plan Title=FEMA Effective June 2007
Short Identifier=FEMAeff0607
Geom File=g01
Flow File=f01
Encroach Param=-1 ,0,0, 0
IC Time=0

--- K111-03-00.p04 (plan) ---

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Plan Title=Storage Routing
Short Identifier=Store_Rout
Geom File=g01
Flow File=f04
Encroach Param=-1 ,0,0, 0

--- K111-03-00.f02 (steady flow) ---

Flow Title=Floodway
Version=Version 3.0.1  Mar 2001
Number of Profiles= 2
Profile Names=1PCT_100yr, 1PCTFloodway_100yrFW
River Rch & RM=K111-03-00,K111-03-00_0003,2255.6
    1510    1510
River Rch & RM=K111-03-00,K111-03-00_0003,2064.60
    1580    1580
River Rch & RM=K111-03-00,K111-03-00_0003,1314.60
    1670    1670
River Rch & RM=K111-03-00,K111-03-00_0003,523.6
    1693    1693
Boundary for River Rch & Prof#=K111-03-00,K111-03-00_0003, 1
Up Type= 0
Dn Type= 3
Dn Slope=.00031
Boundary for River Rch & Prof#=K111-03-00,K111-03-00_0003, 2
Up Type= 0
Dn Type= 3
Dn Slope=.00031
DSS Import GetInterval= 0
DSS Import GetPeak= 0
DSS Import FillOption= 0

--- K111-03-00.f01 (steady flow) ---

Flow Title=FEMA Effective June 2007
Version=Version 3.0.1  Mar 2001
Number of Profiles= 4
Profile Names=10PCT_10yr, 2PCT_50yr, 1PCT_100yr, 0.2PCT_500yr
River Rch & RM=K111-03-00,K111-03-00_0003,2255.6
     760    1260    1510    2070
River Rch & RM=K111-03-00,K111-03-00_0003,2064.60
     810    1320    1580    2230
River Rch & RM=K111-03-00,K111-03-00_0003,1314.60
     880    1400    1670    2440
River Rch & RM=K111-03-00,K111-03-00_0003,523.6
     894    1424    1693    2496
Boundary for River Rch & Prof#=K111-03-00,K111-03-00_0003, 1
Up Type= 0
Dn Type= 3
Dn Slope=.00031
Boundary for River Rch & Prof#=K111-03-00,K111-03-00_0003, 2
Up Type= 0
Dn Type= 3
Dn Slope=.00031
Boundary for River Rch & Prof#=K111-03-00,K111-03-00_0003, 3
Up Type= 0
Dn Type= 3
Dn Slope=.00031
Boundary for River Rch & Prof#=K111-03-00,K111-03-00_0003, 4
Up Type= 0
Dn Type= 3
Dn Slope=.00031
DSS Import GetInterval= 0
DSS Import GetPeak= 0
DSS Import FillOption= 0

--- K111-03-00.f04 (steady flow) ---

Flow Title=Storage Routing
Version=Version 3.0.1  Mar 2001
Number of Profiles= 8
Profile Names=0.25*10% flood, 0.50*10%flood, 10% flood, 2% flood, 1% flood, 0.2%flood, 1.25*0.2% flood
River Rch & RM=K111-03-00,K111-03-00_0003,2255.6
     118     235     470     580     680     800     980    1225
River Rch & RM=K111-03-00,K111-03-00_0003,2116.30
     118     235     470     580     680     800     980    1225
River Rch & RM=K111-03-00,K111-03-00_0003,2064.60
     163     325     650     780     900    1030    1270    1588
Boundary for River Rch & Prof#=K111-03-00,K111-03-00_0003, 1
Up Type= 0
Dn Type= 3
Dn Slope=.00031
Boundary for River Rch & Prof#=K111-03-00,K111-03-00_0003, 2
Up Type= 0
Dn Type= 3
Dn Slope=.00031
Boundary for River Rch & Prof#=K111-03-00,K111-03-00_0003, 3
Up Type= 0
Dn Type= 3
Dn Slope=.00031
Boundary for River Rch & Prof#=K111-03-00,K111-03-00_0003, 4
Up Type= 0
Dn Type= 3
Dn Slope=.00031
Boundary for River Rch & Prof#=K111-03-00,K111-03-00_0003, 5
Up Type= 0
Dn Type= 3
Dn Slope=.00031
Boundary for River Rch & Prof#=K111-03-00,K111-03-00_0003, 6
Up Type= 0
Dn Type= 3
Dn Slope=.00031
Boundary for River Rch & Prof#=K111-03-00,K111-03-00_0003, 7
Up Type= 0
Dn Type= 3
Dn Slope=.00031
Boundary for River Rch & Prof#=K111-03-00,K111-03-00_0003, 8
Up Type= 0
Dn Type= 3
Dn Slope=.00031
DSS Import GetInterval= 0
DSS Import GetPeak= 0
DSS Import FillOption= 0

--- K111-03-00.g01 (geometry) ---

Geom Title=K111-03-00 June 2007
Version=Version 3.0.1  Mar 2001

River Reach=K111-03-00      ,K111-03-00_0003
Reach XY= 30
      3125615.55     13930605.61      3124255.83     13930566.98
      3123058.34     13930505.18      3122698.67     13930509.82
      3122160.83     13930492.36      3121953.56     13930470.41
      3120721.84      13930451.6      3119732.42     13930412.47
       3119516.1     13930412.47      3119481.34     13930424.06
      3119477.47     13930767.85      3119496.79     13930845.11
      3119481.34     13931192.76      3119512.24     13931366.59
       3119682.2     13931640.86      3120018.27     13932100.54
      3120072.35     13932193.24      3120118.71     13932351.62
       3120073.4     13932556.62      3119909.51     13933048.26
      3119858.05     13933298.04      3119796.99     13933387.99
      3119788.31     13933473.06      3119650.29     13933863.68
      3119625.12     13933983.48      3119624.25       13934105.
      3119660.71     13934291.64      3119707.58     13934394.93
      3119727.76     13934499.26      3119721.75       13934561.

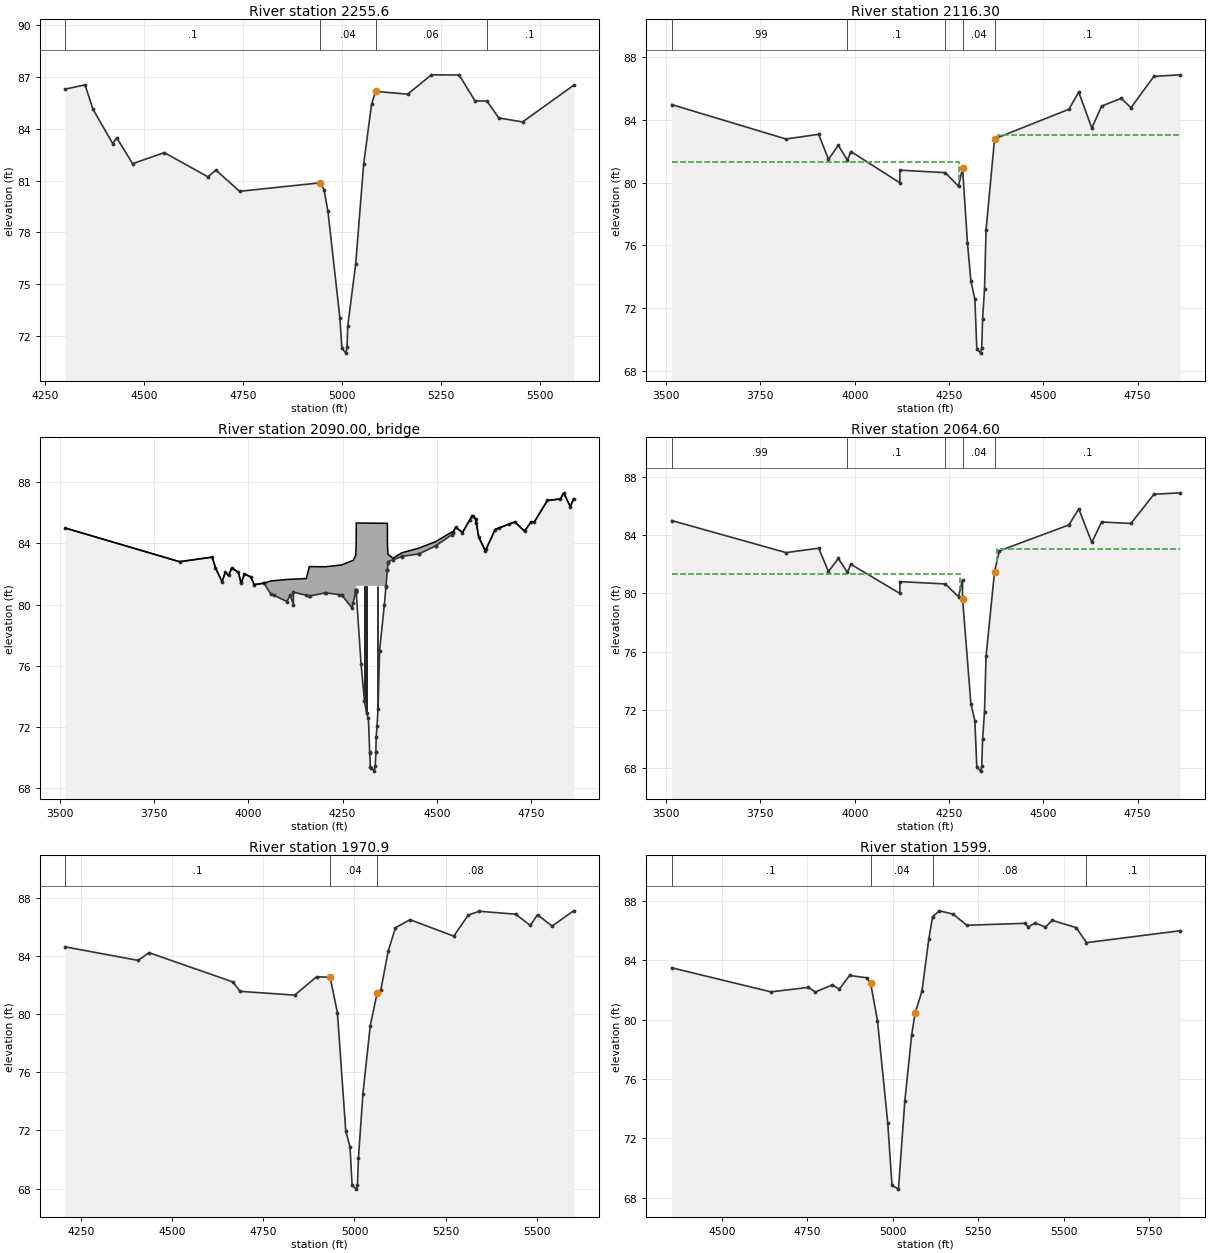
Type RM Length L Ch R = 1 ,2255.6  ,103,139.3,159.4
BEGIN DESCRIPTION:
K111-03-00-S4 TOPO - FARRELL RD DS - XS 4
END DESCRIPTION:
XS GIS Cut Line= 4
      3119520.47      13932027.1      3120043.34      13932383.7
      3120222.73     13932449.33      3120588.64     13932725.56
#Sta/Elev= 30
  4301.9    86.3  4351.9   86.55  4371.9   85.14  4421.9   83.14  4431.9   83.48
  4471.9   81.98  4551.9   82.62  4661.9   81.22  4681.9   81.61  4741.9   80.38
  4944.8   80.87  4954.8   80.48  4964.8   79.21  4994.8   73.05 4999.78   71.29
    5010      715012.858   71.33  5014.8    72.6  5034.8   76.18  5054.8   81.95
  5074.8   85.43  5084.8   86.17  5165.8   86.01  5225.8   87.13  5295.8   87.12
  5335.8   85.62  5365.8   85.61  5395.8   84.63  5455.8    84.4  5584.3   86.52
#Mann= 4 ,-1 , 0
  4301.9      .1       0  4944.8     .04       0  5084.8     .06       0
  5365.8      .1       0
Bank Sta=4944.8,5084.8
XS Rating Curve= 0
Exp/Cntr=.5,.3

Type RM Length L Ch R = 1 ,2116.30 ,51.7,51.7,51.7
BEGIN DESCRIPTION:
Upstream Section of Bridge/Culvert/Weir
END DESCRIPTION:
XS GIS Cut Line= 4
      3119365.97      13932168.9      3119810.46     13932241.69
      3120166.11     13932644.58      3120547.27      13932905.2
#Sta/Elev= 30
3514.764   84.993817.873   82.793904.476   83.093930.456   81.493956.437   82.39
3980.686   81.443989.866   81.994119.683   79.99 4119.77    80.84240.061   80.64
4275.135   79.774285.874   80.94 4298.95   76.134308.044   73.714318.523   72.57
4323.631    69.44333.851   69.114336.709   69.444339.047   71.31 4344.07   73.19
 4348.14   76.984370.744    82.84567.852   84.694593.832   85.794628.473   83.49
4654.453   84.894706.416   85.394732.396   84.794793.017   86.79  4862.3   86.89
#Mann= 5 ,-1 , 0
3514.764     .99       03980.686      .1       04240.061     .04       0
4285.874     .04       04370.744      .1       0
#XS Ineff= 2 , 0
       04277.213    81.34379.404       0   83.03
Permanent Ineff=
       F       F
Bank Sta=4285.874,4370.744
XS Rating Curve= 0
Skew Angle= 30
Exp/Cntr=.5,.3

Type RM Length L Ch R = 3 ,2090.00 ,,,
BEGIN DESCRIPTION:
FARREL ROAD; Piers from nearby pipeline shown on this structure VRR
Structure ID: K111-03-00-S4
END DESCRIPTION:
Bridge Culvert--1,0,-1,-1, 0
Deck Dist Width WeirC Skew NumUp NumDn MinLoCord MaxHiCord MaxSubmerge Is_Ogee
10,30,2.6,30, 56, 55, , , .95, 0, ,,,
 3514.76 3817.87 3904.48 3913.14 3930.46 3939.12 3947.78 3956.44 3973.76 3981.21
 3989.87 4007.19 4015.85 4041.83 4059.15 4102.45 4111.11 4119.68 4119.77 4153.89
 4161.86  4204.9 4247.51 4275.14 4278.25 4285.09 4285.71 4286.13 4286.22 4365.12
 4368.84 4368.93 4370.31 4370.74 4383.39 4407.03 4452.58 4496.58 4539.45 4543.69
 4550.19 4567.85 4593.83 4602.49 4611.15 4628.47 4654.45 4706.42  4732.4 4749.72
 4758.38 4793.02 4827.66 4836.32 4853.64  4862.3
      85    82.8    83.1    82.4    81.5    82.1    81.9    82.4    82.1    81.4
      82    81.8    81.3    81.4   81.54   81.64   81.65   81.66   81.66    81.7
   82.48   82.47   82.59   82.86   82.89   83.21    83.7   84.03   85.33   85.31
   85.31   84.01   83.29   83.28   83.03   83.38   83.69   84.11   84.74   84.76
   85.06   84.71   85.81   85.61   84.41   83.51   84.91    85.4    84.8    85.4
    85.4    86.8    86.9    87.3    86.4    86.9
      85    82.8    83.1    82.4    81.5    82.1    81.9    82.4    82.1    81.4
      82    81.8    81.3    81.4    80.7    80.2    80.6      80   80.81   80.61
   80.57   80.77   80.63   79.78   80.12   80.87   80.93   81.23   81.23   81.21
   82.27   82.29   82.69   82.81   82.92   83.14   83.31   83.83   84.56   84.75
   85.05    84.7    85.8    85.6    84.4    83.5    84.9    85.4    84.8    85.4
    85.4    86.8    86.9    87.3    86.4    86.9
 3514.76 3817.87 3904.48 3913.14 3930.46 3939.12 3947.78 3956.44 3973.76 3981.21
 3989.87 4007.19 4015.85 4041.83 4059.15 4102.45 4111.11 4119.68 4119.77 4153.89
 4161.86  4204.9 4247.51 4275.14 4278.25 4285.09 4285.71 4286.13 4286.22 4368.84
 4368.93 4370.31 4370.74 4383.39 4407.03 4452.58 4496.58 4539.45 4543.69 4550.19
 4567.85 4593.83 4602.49 4611.15 4628.47 4654.45 4706.42  4732.4 4749.72 4758.38
 4793.02 4827.66 4836.32 4853.64  4862.3
      85    82.8    83.1    82.4    81.5    82.1    81.9    82.4    82.1    81.4
      82    81.8    81.3    81.4   81.54   81.64   81.65   81.66   81.66    81.7
   82.48   82.47   82.59   82.86   82.89   83.21    83.7   84.03   85.33   85.31
   84.01   83.29   83.28   83.03   83.38   83.69   84.11   84.74   84.76   85.06
   84.71   85.81   85.61   84.41   83.51   84.91    85.4    84.8    85.4    85.4
    86.8    86.9    87.3    86.4    86.9
      85    82.8    83.1    82.4    81.5    82.1    81.9    82.4    82.1    81.4
      82    81.8    81.3    81.4    80.7    80.2    80.6      80   80.81   80.61
   80.57   80.77   80.63   79.78   80.12   80.87   80.93   81.23   81.23   81.21
   81.21   81.21   81.21   82.92   83.14   83.31   83.83   84.56   84.75   85.05
    84.7    85.8    85.6    84.4    83.5    84.9    85.4    84.8    85.4    85.4
    86.8    86.9    87.3    86.4    86.9
Pier Skew, UpSta & Num, DnSta & Num=  ,4308.044, 2 ,4308.044, 2 , 0 , 0 , 0 ,,
     1.3     1.3
   72.63   82.22
     1.3     1.3
   71.29   82.22
Pier Skew, UpSta & Num, DnSta & Num=  ,4313.499, 2 ,4313.499, 2 , 0 , 0 , 0 ,,
     1.3     1.3
   71.86   82.22
     1.3     1.3
   70.52   82.22
Pier Skew, UpSta & Num, DnSta & Num=  ,4341.472, 2 ,4341.472, 2 , 0 , 0 , 0 ,,
     1.3     1.3
   70.92   82.22
     1.3     1.3
   69.58   82.22
Pier Skew, UpSta & Num, DnSta & Num=  ,4344.07, 2 ,4344.07, 2 , 0 , 0 , 0 ,,
     1.3     1.3
   71.96   82.22
     1.3     1.3
   70.62   82.22
BR Coef= 1 , 1 , 1 ,.9, 0 ,,,.8,-1,1.2,0,
WSPro=,,,, 1 ,,,, 0 ,,,, 0 ,,,,-1 ,-1 ,-1 , 0 , 0 , 0 , 0 , 0
BR U #Sta/Elev= 95
 3514.76      85 3817.87    82.8 3904.48    83.1 3913.14    82.4 3930.46    81.5
 3939.12    82.1 3947.78    81.9 3956.44    82.4 3973.76    82.1 3980.69   81.45
 3981.21    81.4 3989.87      82 4007.19    81.8 4015.85    81.3 4041.31    81.4
 4041.83    81.4 4059.15    80.7 4067.29   80.61 4102.45    80.2 4111.11    80.6
 4119.68      80 4119.77   80.81 4153.89   80.61 4161.86   80.57 4163.07   80.56
 4203.08   80.76  4204.9   80.77 4240.06   80.65 4247.42   80.63 4247.51   80.63
 4275.14   79.78 4278.25   80.12 4285.09   80.87 4285.71   80.93 4285.79   80.94
 4285.87   80.95 4286.13   80.86 4286.22   80.82 4286.31   80.79 4298.95   76.14
 4308.04   73.72  4313.5   72.89 4318.52   72.58  4321.9   70.38 4321.99   70.32
 4323.63   69.41 4326.32   69.34 4333.85   69.12 4336.71   69.45 4338.27   70.34
 4338.35   70.39 4339.05   71.32 4341.47    72.1 4344.07    73.2 4348.14   76.99
 4360.87      80 4365.02   81.18 4365.12   81.21 4368.74   82.24 4368.84   82.27
 4368.93   82.29 4370.31   82.69 4370.74   82.81 4383.39   82.92 4407.03   83.14
 4408.59   83.15 4452.24   83.31 4452.58   83.31 4496.58   83.83  4497.7   83.85
 4539.45   84.56  4542.3   84.69 4543.69   84.75 4550.19   85.05 4567.85    84.7
 4586.99   85.51 4593.83    85.8 4595.65   85.76 4602.49    85.6 4604.31   85.35
 4611.15    84.4 4628.47    83.5 4630.29    83.6 4654.45    84.9 4664.93      85
 4690.91   85.25 4706.42    85.4  4732.4    84.8 4749.72    85.4 4758.38    85.4
 4793.02    86.8 4827.66    86.9 4836.32    87.3 4853.64    86.4  4862.3    86.9
BR U #Mann= 5
 3514.76     .99 3980.69      .1 4240.06     .04 4285.87     .04 4370.74      .1
BR U Banks=4285.87,4370.74
BR D #Sta/Elev= 95
 3514.76      85 3817.87    82.8 3904.48    83.1 3913.14    82.4 3930.46    81.5
 3939.12    82.1 3947.78    81.9 3956.44    82.4 3973.76    82.1 3980.69   81.45
 3981.21    81.4 3989.87      82 4007.19    81.8 4015.85    81.3 4041.31    81.4
 4041.83    81.4 4059.15    80.7 4067.29   80.61 4102.45    80.2 4111.11    80.6
 4119.68      80 4119.77   80.81 4153.89   80.61 4161.86   80.57 4163.07   80.56
 4203.08   80.76  4204.9   80.77 4240.06   80.65 4247.42   80.63 4247.51   80.63
 4275.14   79.78 4278.25   80.12 4285.09   80.87 4285.71   80.93 4285.79   80.94
 4285.87   79.61 4286.13   79.52 4286.22   79.48 4286.31   79.45 4298.95    74.8
 4308.04   72.38  4313.5   71.55 4318.52   71.24  4321.9   69.04 4321.99   68.98
 4323.63   68.07 4326.32      68 4333.85   67.78 4336.71   68.11 4338.27      69
 4338.35   69.05 4339.05   69.98 4341.47   70.76 4344.07   71.86 4348.14   75.65
 4360.87   78.66 4365.02   79.84 4365.12   79.87 4368.74    80.9 4368.84   80.93
 4368.93   80.95 4370.31   81.35 4370.74   81.47 4383.39   82.92 4407.03   83.14
 4408.59   83.15 4452.24   83.31 4452.58   83.31 4496.58   83.83  4497.7   83.85
 4539.45   84.56  4542.3   84.69 4543.69   84.75 4550.19   85.05 4567.85    84.7
 4586.99   85.51 4593.83    85.8 4595.65   85.76 4602.49    85.6 4604.31   85.35
 4611.15    84.4 4628.47    83.5 4630.29    83.6 4654.45    84.9 4664.93      85
 4690.91   85.25 4706.42    85.4  4732.4    84.8 4749.72    85.4 4758.38    85.4
 4793.02    86.8 4827.66    86.9 4836.32    87.3 4853.64    86.4  4862.3    86.9
BR D #Mann= 5
 3514.76     .99 3980.69      .1 4240.06     .04 4285.87     .04 4370.74      .1
BR D Banks=4285.87,4370.74
BC Design=,, 0 ,, 0 ,,,,,,
BC HTab HWMax=87.29

Type RM Length L Ch R = 1 ,2064.60 ,135,93.7,39
BEGIN DESCRIPTION:
Downstream Section of Bridge/Culvert/Weir
END DESCRIPTION:
XS GIS Cut Line= 4
      3119356.84      13932214.1      3119787.81     13932284.65
      3120138.86     13932682.31      3120530.35      13932951.2
#Sta/Elev= 30
3514.764   84.993817.873   82.793904.476   83.093930.456   81.493956.437   82.39
3980.686   81.443989.866   81.994119.683   79.99 4119.77    80.84240.061   80.64
4275.135   79.774285.787   80.934285.874   79.634308.044    72.44318.523   71.26
4323.631   68.094333.851    67.84336.709   68.134339.047      70 4344.07   71.88
 4348.14   75.674370.744   81.494383.388   82.914567.852   84.694593.832   85.79
4628.473   83.494654.453   84.894732.396   84.794793.017   86.79  4862.3   86.89
#Mann= 5 ,-1 , 0
3514.764     .99       03980.686      .1       04240.061     .04       0
4285.874     .04       04370.744      .1       0
#XS Ineff= 2 , 0
       04280.097    81.3 4376.52       0   83.03
Permanent Ineff=
       F       F
Bank Sta=4285.874,4370.744
XS Rating Curve= 0
Skew Angle= 30
Exp/Cntr=.5,.3

Type RM Length L Ch R = 1 ,1970.9  ,371,371.9,372
BEGIN DESCRIPTION:
K111-03-00-S4 TOPO - FARRELL RD DS - XS 1
END DESCRIPTION:
XS GIS Cut Line= 4
      3119326.06     13932306.51      3119963.09     13932657.18
      3120085.52     13932698.99      3120499.57     13933043.66
#Sta/Elev= 30
    4206   84.63    4406    83.7    4436   84.23    4666   82.22    4686   81.57
    4836   81.31    4896   82.57  4933.2   82.54  4953.2   80.09 4976.09   71.96
 4987.83   70.86 4993.55   68.21    5005   67.96 5008.24   68.26 5010.88    70.1
  5023.2   74.53  5043.2   79.19  5062.5   81.49  5072.5   81.69  5092.5   84.33
  5112.5   85.95  5152.5    86.5  5272.5   85.37  5312.5   86.82  5342.5   87.08
  5442.5   86.88  5482.5   86.11  5502.5   86.84  5542.5   86.06  5601.3   87.11
#Mann= 3 ,-1 , 0
    4206      .1       0  4933.2     .04       0  5062.5     .08       0
Bank Sta=4933.2,5062.5
XS Rating Curve= 0
Exp/Cntr=.3,.1

Type RM Length L Ch R = 1 ,1599.   ,54,105.3,186
BEGIN DESCRIPTION:
K111-03-00-S3 TOPO - E RICHEY RD US - XS 4
END DESCRIPTION:
XS GIS Cut Line= 4
      3119477.67     13932567.85      3119853.53     13933011.83
      3120024.48     13933071.53      3120454.05     13933653.61
#Sta/Elev= 30
  4353.3   83.48  4643.3   81.86  4753.3   82.16  4773.3   81.85  4823.3   82.33
  4843.3   82.04  4873.3   82.96  4923.3   82.81    4935   82.44    4955   79.93
    4985   73.06 4997.38   68.85 5016.34   68.59    5035   74.53    5055   78.97
    5065   80.43    5085    81.9    5105   85.39  5116.1   86.92  5136.1   87.31
  5176.1   87.09  5216.1   86.34  5386.1   86.47  5396.1   86.23  5416.1   86.49
  5446.1   86.22  5466.1   86.67  5536.1   86.18  5566.1   85.17  5839.5   85.97
#Mann= 4 ,-1 , 0
  4353.3      .1       0    4935     .04       0  5116.1     .08       0
  5566.1      .1       0
Bank Sta=4935,5065
XS Rating Curve= 0
Exp/Cntr=.5,.3

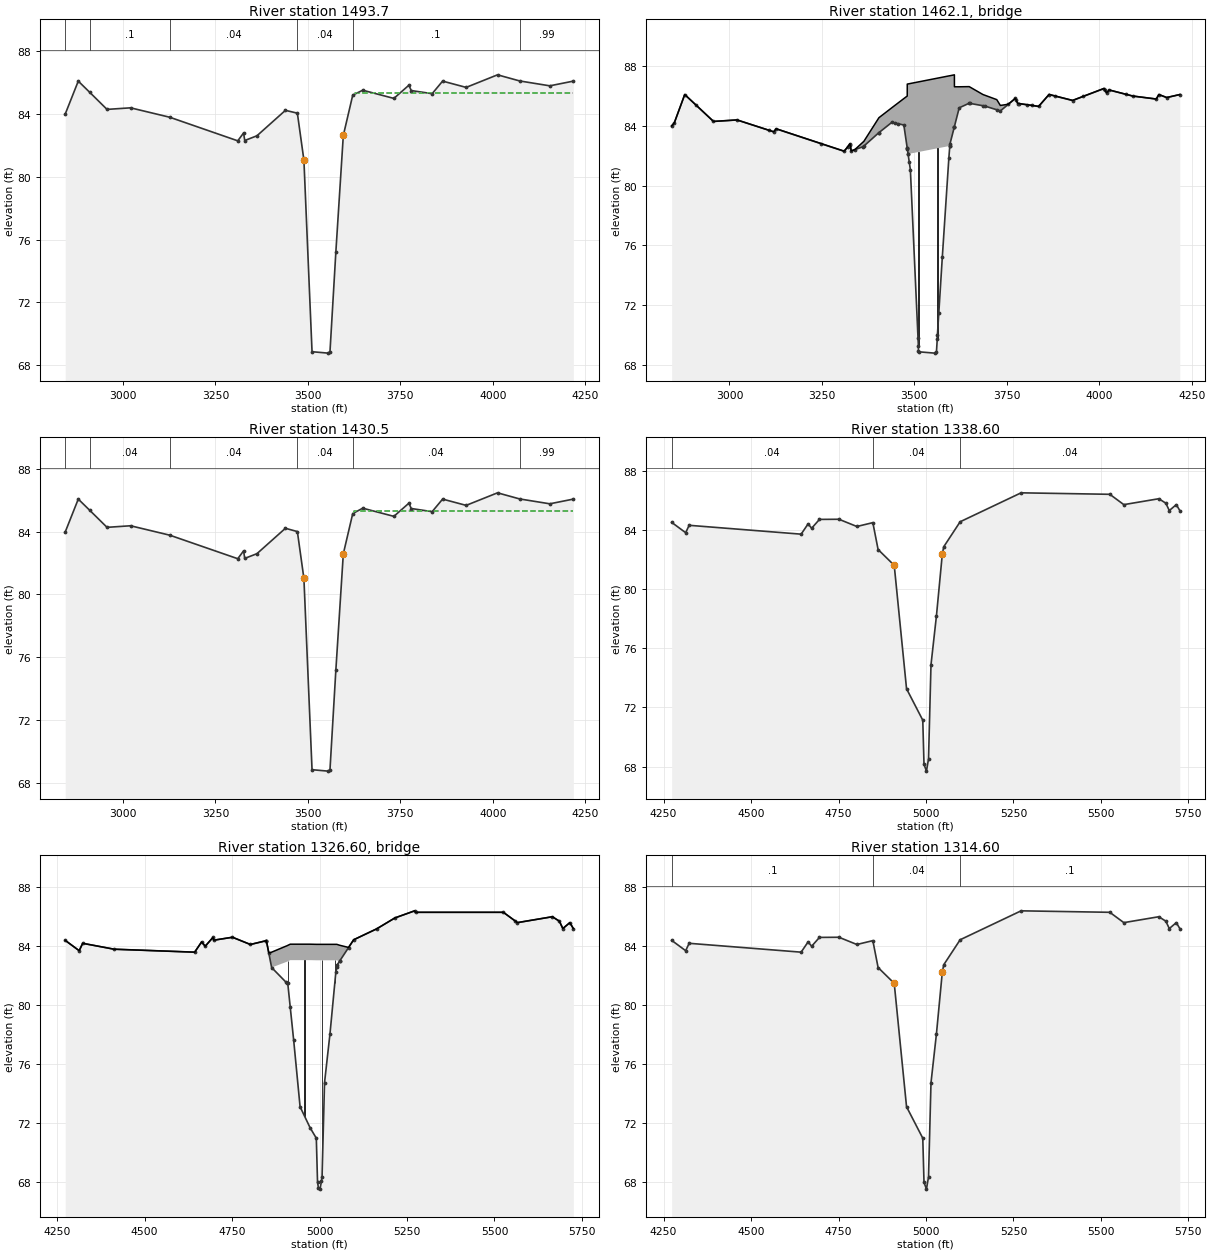
Type RM Length L Ch R = 1 ,1493.7  ,63.2,63.2,63.2
BEGIN DESCRIPTION:
Upstream Section of Bridge/Culvert/Weir
END DESCRIPTION:
XS GIS Cut Line= 4
      3119446.88       13932667.      3119712.81     13932897.53
      3120092.17     13933414.42      3120423.26      13933752.8
#Sta/Elev= 30
2843.701   83.982879.056   86.082909.462   85.382956.838   84.283020.477   84.38
3126.543   83.783310.391   82.283326.159   82.783329.271    82.33362.222    82.6
3439.297   84.223471.612   84.043489.289   81.05 3511.28   68.863554.767   68.77
3559.787   68.853575.697   75.213595.857   82.623621.376   85.193648.388    85.5
3732.605   84.983773.263   85.823779.556   85.483836.125   85.283864.409   86.08
3928.049   85.684012.902   86.484072.864   86.094154.323   85.784217.963   86.08
#Mann= 6 ,-1 , 0
2843.701     .99       02909.462      .1       03126.543     .04       0
3471.612     .04       03621.376      .1       04072.864     .99       0
#XS Ineff= 2 , 0
       0 3464.54   82.313628.448       0   85.31
Permanent Ineff=
       F       F
Bank Sta=3489.289,3595.857
XS Rating Curve= 0
Skew Angle= 45
Exp/Cntr=.5,.3

Type RM Length L Ch R = 3 ,1462.1  ,,,
BEGIN DESCRIPTION:
RICHEY ROAD
Structure ID: K111-03-00-S3
END DESCRIPTION:
Bridge Culvert--1,0,-1,-1, 0
Deck Dist Width WeirC Skew NumUp NumDn MinLoCord MaxHiCord MaxSubmerge Is_Ogee
10,43.2,2.6,45, 41, 41, , , .95, 0, ,,,
  2843.7 2850.77 2879.06 2956.84 3020.48 3119.47 3126.54 3310.39 3326.16 3329.27
 3339.38 3363.57 3404.22  3439.3 3471.61  3480.8 3480.88 3483.07 3595.94 3596.35
 3608.37 3608.44 3621.38 3648.39 3685.65 3722.92 3732.61 3753.89 3773.26 3779.56
 3836.13 3864.41 3928.05  4012.9 4019.97 4027.04 4090.68 4154.32 4161.39 4182.61
 4217.96
      84    84.2    86.1    84.3    84.4   83.61   83.81   82.31   82.81   82.32
   82.42   82.97   84.55   85.22   85.83      86    86.8   86.81   87.36   87.36
   87.42   86.62   86.62   86.63    86.1   85.76   85.37   85.45   85.85   85.51
   85.31   86.11   85.71   86.51   86.21   86.41      86    85.8    86.1    85.9
    86.1
      84    84.2    86.1    84.3    84.4    83.6    83.8    82.3    82.8   82.32
   82.41   82.65   83.55   84.24   84.06   82.51   82.49   82.12   82.66   82.79
   83.95   83.96   85.21   85.52   85.35   85.08      85   85.44   85.84    85.5
    85.3    86.1    85.7    86.5    86.2    86.4      86    85.8    86.1    85.9
    86.1
  2843.7 2850.77 2879.06 2956.84 3020.48 3119.47 3126.54 3310.39 3326.16 3329.27
 3339.38 3363.57 3404.22  3439.3 3471.61  3480.8 3480.88 3483.07 3595.94 3596.35
 3608.37 3608.44 3621.38 3648.39 3685.65 3722.92 3732.61 3753.89 3773.26 3779.56
 3836.13 3864.41 3928.05  4012.9 4019.97 4027.04 4090.68 4154.32 4161.39 4182.61
 4217.96
      84    84.2    86.1    84.3    84.4   83.61   83.81   82.31   82.81   82.32
   82.42   82.97   84.55   85.22   85.83      86    86.8   86.81   87.36   87.36
   87.42   86.62   86.62   86.63    86.1   85.76   85.37   85.45   85.85   85.51
   85.31   86.11   85.71   86.51   86.21   86.41      86    85.8    86.1    85.9
    86.1
      84    84.2    86.1    84.3    84.4    83.6    83.8    82.3    82.8   82.32
   82.41   82.65   83.55   84.24   84.06   82.51   82.49   82.12   82.66   82.79
   83.95   83.96   85.21   85.52   85.35   85.08      85   85.44   85.84    85.5
    85.3    86.1    85.7    86.5    86.2    86.4      86    85.8    86.1    85.9
    86.1
Pier Skew, UpSta & Num, DnSta & Num=  ,3510.997, 2 ,3510.997, 2 , 0 , 0 , 0 ,,
     1.7     1.7
   67.88   83.25
     1.7     1.7
   67.97   83.34
Pier Skew, UpSta & Num, DnSta & Num=  ,3562.05, 2 ,3562.05, 2 , 0 , 0 , 0 ,,
     1.7     1.7
   68.52    83.5
     1.7     1.7
   68.61   83.59
BR Coef= 1 , 1 , 1 ,1.25, 0 ,,,.8,-1,2,0,
WSPro=,,,, 1 ,,,, 0 ,,,, 0 ,,,,-1 ,-1 ,-1 , 0 , 0 , 0 , 0 , 0
BR U #Sta/Elev= 77
  2843.7      84 2850.77    84.2 2879.06    86.1 2909.46    85.4 2956.84    84.3
 3020.48    84.4 3107.45    83.7 3119.47    83.6 3126.54    83.8 3248.87    82.8
 3310.39    82.3 3319.58   82.59 3326.16    82.8 3326.66   82.72 3329.27   82.32
 3339.38   82.41 3362.22   82.62 3363.57   82.65 3404.22   83.55  3404.3   83.55
  3439.3   84.24  3447.5   84.19 3457.05   84.14 3471.61   84.06  3480.8   82.51
 3480.88   82.49 3480.95   82.48    3483   82.13 3483.07   82.12 3486.32   81.57
 3489.29   81.07 3510.01   69.78    3511   69.26 3511.21   68.93 3511.28   68.88
 3554.77   68.79 3559.79   68.87 3562.05   69.75  3562.4      70 3566.15   71.47
  3575.7   75.23 3593.45   81.88 3595.86   82.64 3595.94   82.66 3596.35   82.79
 3608.29   83.94 3608.37   83.95 3608.44   83.96 3621.38   85.21 3648.39   85.52
  3649.8   85.51 3685.65   85.35 3690.53   85.33 3722.92   85.08 3732.61      85
 3753.89   85.44 3773.26   85.84  3775.1   85.74 3779.56    85.5 3782.17   85.49
 3803.39   85.42 3817.53   85.37 3836.13    85.3 3864.41    86.1 3881.17   85.99
 3928.05    85.7 3956.55   85.97  4012.9    86.5 4015.52   86.39 4019.97    86.2
 4027.04    86.4 4072.86   86.11 4090.68      86 4154.32    85.8 4161.39    86.1
 4182.61    85.9 4217.96    86.1
BR U #Mann= 6
  2843.7     .99 2909.46      .1 3126.54     .04 3471.61     .04 3621.38      .1
 4072.86     .99
BR U Banks=3489.29,3595.86
BR D #Sta/Elev= 77
  2843.7      84 2850.77    84.2 2879.06    86.1 2909.46    85.4 2956.84    84.3
 3020.48    84.4 3107.45    83.7 3119.47    83.6 3126.54    83.8 3248.87    82.8
 3310.39    82.3 3319.58   82.59 3326.16    82.8 3326.66   82.72 3329.27   82.32
 3339.38   82.41 3362.22   82.62 3363.57   82.65 3404.22   83.55  3404.3   83.55
  3439.3   84.24  3447.5   84.19 3457.05   84.14 3471.61   84.15  3480.8    82.6
 3480.88   82.58 3480.95   82.57    3483   82.22 3483.07   82.21 3486.32   81.66
 3489.29   81.16 3510.01   69.87    3511   69.35 3511.21   69.02 3511.28   68.97
 3554.77   68.88 3559.79   68.96 3562.05   69.84  3562.4   70.09 3566.15   71.56
  3575.7   75.32 3593.45   81.97 3595.86   82.73 3595.94   82.75 3596.35   82.88
 3608.29   84.03 3608.37   84.04 3608.44   84.05 3621.38    85.3 3648.39   85.52
  3649.8   85.51 3685.65   85.35 3690.53   85.33 3722.92   85.08 3732.61      85
 3753.89   85.44 3773.26   85.84  3775.1   85.74 3779.56    85.5 3782.17   85.49
 3803.39   85.42 3817.53   85.37 3836.13    85.3 3864.41    86.1 3881.17   85.99
 3928.05    85.7 3956.55   85.97  4012.9    86.5 4015.52   86.39 4019.97    86.2
 4027.04    86.4 4072.86   86.11 4090.68      86 4154.32    85.8 4161.39    86.1
 4182.61    85.9 4217.96    86.1
BR D #Mann= 5
  2843.7     .99 2909.46     .04 3471.61     .04 3621.38     .04 4072.86     .99
BR D Banks=3489.29,3595.86
BC Design=,, 0 ,, 0 ,,,,,,
BC HTab HWMax=86.48

Type RM Length L Ch R = 1 ,1430.5  ,91,91.9,92
BEGIN DESCRIPTION:
Downstream Section of Bridge/Culvert/Weir
END DESCRIPTION:
XS GIS Cut Line= 4
      3119414.14      13932711.2      3119683.98     13932945.13
      3120062.61     13933461.02      3120391.88      13933797.5
#Sta/Elev= 30
2843.701   83.982879.056   86.082909.462   85.382956.838   84.283020.477   84.38
3126.543   83.783310.391   82.283326.159   82.783329.271    82.33362.222    82.6
3439.297   84.223471.612   84.013489.289   81.02 3511.28   68.833554.767   68.74
3559.787   68.823575.697   75.183595.857   82.593621.376   85.163648.388    85.5
3732.605   84.983773.263   85.823779.556   85.483836.125   85.283864.409   86.08
3928.049   85.684012.902   86.484072.864   86.094154.323   85.784217.963   86.08
#Mann= 6 ,-1 , 0
2843.701     .99       02909.462     .04       03126.543     .04       0
3471.612     .04       03621.376     .04       04072.864     .99       0
#XS Ineff= 2 , 0
       03466.895   82.313626.093       0   85.31
Permanent Ineff=
       F       F
Bank Sta=3489.289,3595.857
XS Rating Curve= 0
Skew Angle= 45
Exp/Cntr=.5,.3

Type RM Length L Ch R = 1 ,1338.60 ,24,24,24
BEGIN DESCRIPTION:
Upstream Section of Bridge/Culvert/Weir
Channel bank stations moved from 4848.15 and 5097.65 to 4909.25 and 5046.75
END DESCRIPTION:
XS GIS Cut Line= 4
      3119379.27      13932765.4      3119696.93     13933029.56
      3120006.12     13933520.04      3120347.41      13933829.3
#Sta/Elev= 30
  4273.2   84.54  4313.2   83.84  4323.2   84.34  4643.2   83.74  4663.2   84.44
  4673.2   84.14  4695.6   84.74 4751.25   84.75 4802.45   84.26 4848.15   84.52
 4863.15    82.7 4909.25   81.63 4944.45   73.27 4990.85   71.14 4994.35   68.15
 5001.35   67.69 5007.25   68.52 5014.35    74.9 5029.95   78.22 5046.75   82.41
 5050.85   82.89 5097.65   84.58 5271.85   86.54  5525.4   86.44  5565.4   85.74
  5665.4   86.14  5685.4   85.84  5695.4   85.34  5715.4   85.74  5725.4   85.34
#Mann= 3 ,-1 , 0
  4273.2     .04       0 4848.15     .04       0 5097.65     .04       0
#XS Ineff= 2 , 0
       0 4838.15    83.6 5107.65       0   84.44
Permanent Ineff=
       F       F
Bank Sta=4909.25,5046.75
XS Rating Curve= 0
Exp/Cntr=.5,.3

Type RM Length L Ch R = 3 ,1326.60 ,,,
BEGIN DESCRIPTION:
PL1_K111-03-00-S2
END DESCRIPTION:
Bridge Culvert--1,0,-1,-1, 0
Deck Dist Width WeirC Skew NumUp NumDn MinLoCord MaxHiCord MaxSubmerge Is_Ogee
10,1,2.6,0, 50, 50, , , .95, 0, ,,,
  4273.2  4313.2  4323.2  4413.2  4643.2  4663.2  4673.2  4695.6 4697.55 4751.25
 4802.45 4848.15  4848.2 4848.29 4855.05 4863.15 4904.45 4905.75 4909.25 4916.35
 4926.15 4944.45 4973.05 4990.85 4994.35 4997.05 5001.35 5005.65 5007.25 5014.35
 5029.95 5046.75 5049.55 5050.85 5057.27 5057.38    5083 5097.65 5163.45 5215.55
 5271.85  5275.4  5525.4  5559.4  5565.4  5665.4  5685.4  5695.4  5715.4  5725.4
    84.4    83.7    84.2    83.8    83.6    84.3      84    84.6   84.41   84.61
   84.12   84.38   84.37   84.36   83.55    83.6   84.01   84.02   84.06   84.14
   84.14   84.14   84.14   84.13   84.13   84.13   84.13   84.13   84.13   84.13
   84.13   84.13   84.13   84.12   84.07   84.07   83.92   84.44   85.18   85.92
    86.4    86.3    86.3   85.71    85.6      86    85.7    85.2    85.6    85.2
    84.4    83.7    84.2    83.8    83.6    84.3      84    84.6   84.41   84.61
   84.12   84.38   84.37   84.36   83.54   82.56   82.93   82.94   82.98   83.06
   83.06   83.06   83.06   83.05   83.05   83.05   83.05   83.05   83.05   83.05
   83.05   83.05   83.05   83.04   82.99   82.99   83.91   84.44   85.18   85.92
    86.4    86.3    86.3   85.71    85.6      86    85.7    85.2    85.6    85.2
  4273.2  4313.2  4323.2  4413.2  4643.2  4663.2  4673.2  4695.6 4697.55 4751.25
 4802.45 4848.15  4848.2 4848.29 4855.05 4863.15 4904.45 4905.75 4909.25 4916.35
 4926.15 4944.45 4973.05 4990.85 4994.35 4997.05 5001.35 5005.65 5007.25 5014.35
 5029.95 5046.75 5049.55 5050.85 5057.27 5057.38    5083 5097.65 5163.45 5215.55
 5271.85  5275.4  5525.4  5559.4  5565.4  5665.4  5685.4  5695.4  5715.4  5725.4
    84.4    83.7    84.2    83.8    83.6    84.3      84    84.6   84.41   84.61
   84.12   84.38   84.37   84.36   83.55    83.6   84.01   84.02   84.06   84.14
   84.14   84.14   84.14   84.13   84.13   84.13   84.13   84.13   84.13   84.13
   84.13   84.13   84.13   84.12   84.07   84.07   83.92   84.44   85.18   85.92
    86.4    86.3    86.3   85.71    85.6      86    85.7    85.2    85.6    85.2
    84.4    83.7    84.2    83.8    83.6    84.3      84    84.6   84.41   84.61
   84.12   84.38   84.37   84.36   83.54   82.56   82.93   82.94   82.98   83.06
   83.06   83.06   83.06   83.05   83.05   83.05   83.05   83.05   83.05   83.05
   83.05   83.05   83.05   83.04   82.99   82.99   83.91   84.44   85.18   85.92
    86.4    86.3    86.3   85.71    85.6      86    85.7    85.2    85.6    85.2
Pier Skew, UpSta & Num, DnSta & Num=  ,4909.3, 2 ,4909.3, 2 , 0 , 0 , 0 ,,
     1.3     1.3
   80.34   83.99
     1.3     1.3
   80.34   83.99
Pier Skew, UpSta & Num, DnSta & Num=  ,4957.4, 2 ,4957.4, 2 , 0 , 0 , 0 ,,
     1.3     1.3
   71.46   84.06
     1.3     1.3
   71.46   84.06
Pier Skew, UpSta & Num, DnSta & Num=  ,5007.3, 2 ,5007.3, 2 , 0 , 0 , 0 ,,
     1.3     1.3
   67.26   84.05
     1.3     1.3
   67.26   84.05
Pier Skew, UpSta & Num, DnSta & Num=  ,5043.8, 2 ,5043.8, 2 , 0 , 0 , 0 ,,
     1.3     1.3
   80.36   84.05
     1.3     1.3
   80.36   84.05
BR Coef= 1 , 1 , 1 ,1.25, 0 ,,,.8,-1,2,0,
WSPro=,,,, 1 ,,,, 0 ,,,, 0 ,,,,-1 ,-1 ,-1 , 0 , 0 , 0 , 0 , 0
BR U #Sta/Elev= 50
  4273.2    84.4  4313.2    83.7  4323.2    84.2  4413.2    83.8  4643.2    83.6
  4663.2    84.3  4673.2      84  4695.6    84.6 4697.55   84.41 4751.25   84.61
 4802.45   84.12 4848.15   84.38  4848.2   84.37 4848.29   84.36 4855.05   83.54
 4863.15   82.56 4904.45   81.56 4905.75   81.54 4909.25   81.49 4916.35   79.87
 4926.15   77.64 4944.45   73.13 4973.05   71.71 4990.85      71 4994.35   68.01
 4997.05   67.63 5001.35   67.55 5005.65   68.09 5007.25   68.38 5014.35   74.76
 5029.95   78.08 5046.75   82.27 5049.55    82.6 5050.85   82.75 5057.27   82.98
 5057.38   82.99    5083   83.91 5097.65   84.44 5163.45   85.18 5215.55   85.92
 5271.85    86.4  5275.4    86.3  5525.4    86.3  5559.4   85.71  5565.4    85.6
  5665.4      86  5685.4    85.7  5695.4    85.2  5715.4    85.6  5725.4    85.2
BR U #Mann= 3
  4273.2     .04 4848.15     .04 5097.65     .04
BR U Banks=4909.25,5046.75
BR D #Sta/Elev= 50
  4273.2    84.4  4313.2    83.7  4323.2    84.2  4413.2    83.8  4643.2    83.6
  4663.2    84.3  4673.2      84  4695.6    84.6 4697.55   84.41 4751.25   84.61
 4802.45   84.12 4848.15   84.38  4848.2   84.37 4848.29   84.36 4855.05   83.54
 4863.15   82.56 4904.45   81.56 4905.75   81.54 4909.25   81.49 4916.35   79.87
 4926.15   77.64 4944.45   73.13 4973.05   71.71 4990.85      71 4994.35   68.01
 4997.05   67.63 5001.35   67.55 5005.65   68.09 5007.25   68.38 5014.35   74.76
 5029.95   78.08 5046.75   82.27 5049.55    82.6 5050.85   82.75 5057.27   82.98
 5057.38   82.99    5083   83.91 5097.65   84.44 5163.45   85.18 5215.55   85.92
 5271.85    86.4  5275.4    86.3  5525.4    86.3  5559.4   85.71  5565.4    85.6
  5665.4      86  5685.4    85.7  5695.4    85.2  5715.4    85.6  5725.4    85.2
BR D #Mann= 3
  4273.2      .1 4848.15     .04 5097.65     .04
BR D Banks=4909.25,5046.75
BC Design=,, 0 ,, 0 ,,,,,,
BC HTab HWMax=86.54

Type RM Length L Ch R = 1 ,1314.60 ,180,135.7,46
BEGIN DESCRIPTION:
Downstream Section of Bridge/Culvert/Weir
END DESCRIPTION:
XS GIS Cut Line= 4
       3119366.5      13932782.3      3119681.71     13933042.91
      3119990.66     13933533.03      3120329.41    13933839.989
#Sta/Elev= 30
  4273.2   84.37  4313.2   83.67  4323.2   84.17  4643.2   83.57  4663.2   84.27
  4673.2   83.97  4695.6   84.57 4751.25   84.58 4802.45   84.09 4848.15   84.35
 4863.15   82.53 4909.25   81.46 4944.45    73.1 4990.85   70.97 4994.35   67.98
 5001.35   67.52 5007.25   68.35 5014.35   74.73 5029.95   78.05 5046.75   82.24
 5050.85   82.72 5097.65   84.41 5271.85   86.37  5525.4   86.27  5565.4   85.57
  5665.4   85.97  5685.4   85.67  5695.4   85.17  5715.4   85.57  5725.4   85.17
#Mann= 3 ,-1 , 0
  4273.2      .1       0 4848.15     .04       0 5097.65      .1       0
#XS Ineff= 2 , 0
       0 4841.48    83.6 5104.32       0   84.44
Permanent Ineff=
       F       F
Bank Sta=4909.25,5046.75
XS Rating Curve= 0
Exp/Cntr=.5,.3

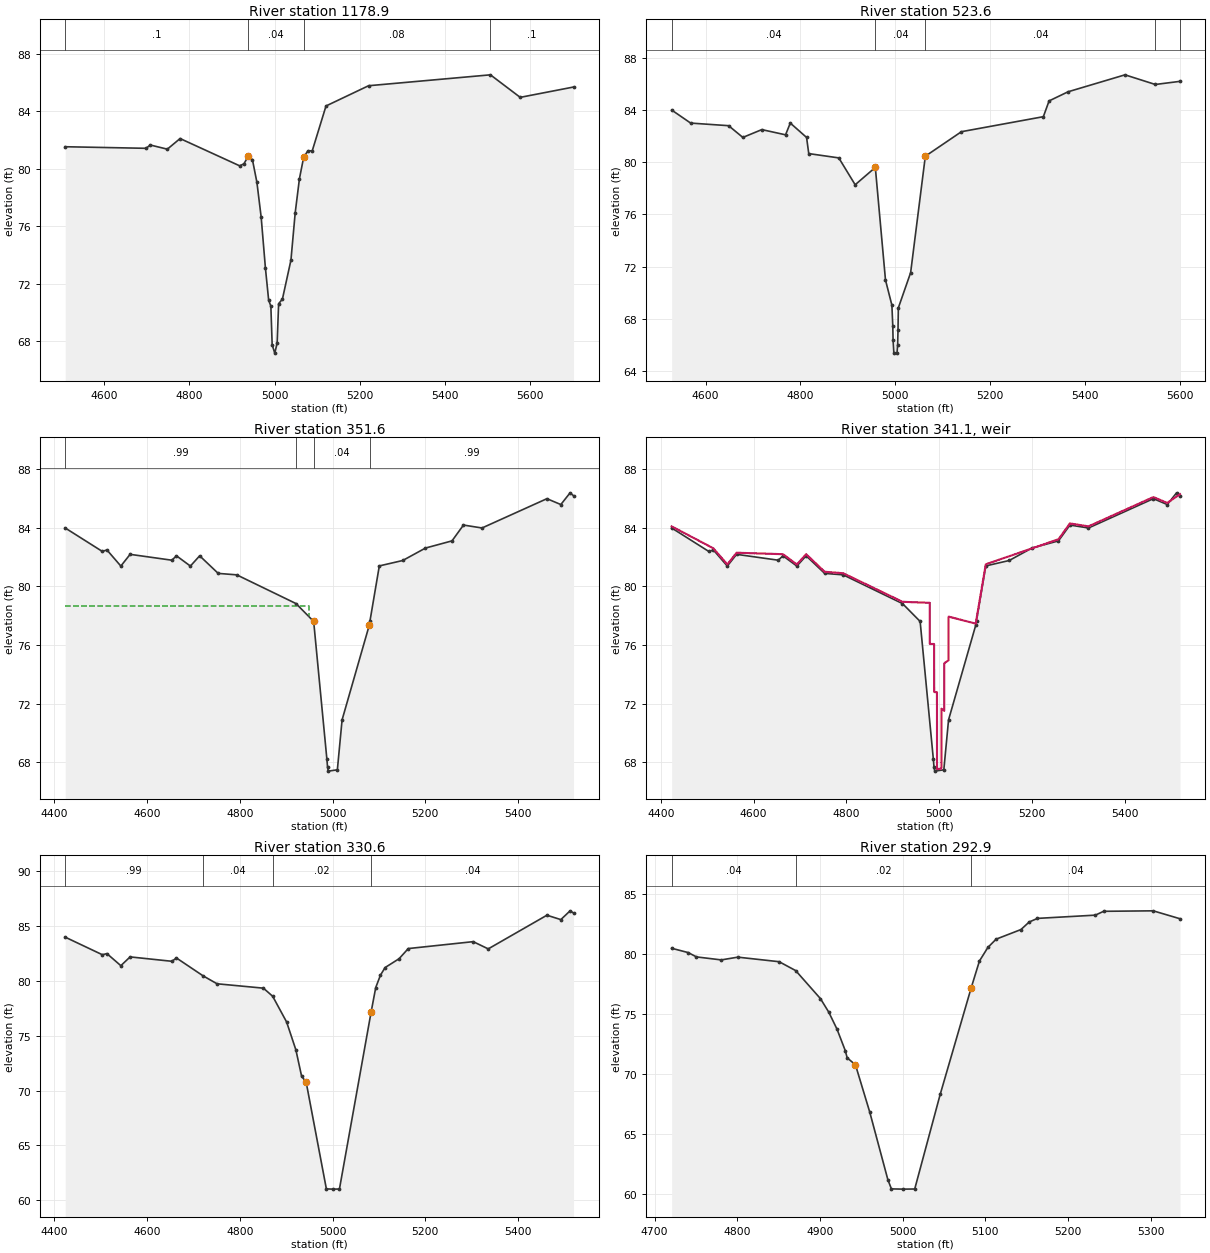
Type RM Length L Ch R = 1 ,1178.9  ,699.21,655.3,612.22
BEGIN DESCRIPTION:
K111-03-00-S1 DS_FIELD - DAM DS - XS 1
END DESCRIPTION:
XS GIS Cut Line= 5
      3119314.28     13933295.92      3119740.47     13933407.23
      3119902.82     13933465.19      3119970.53     13933571.96
      3120306.46     13933879.25
#Sta/Elev= 30
  4508.1   81.53  4698.1   81.42  4708.1   81.65  4748.1   81.36  4778.1    82.1
  4918.1    80.2  4928.1   80.34  4938.1   80.86  4948.1   80.63  4958.6   79.05
  4968.6   76.63  4978.6   73.08 4986.22   70.84 4991.41   70.42 4994.46   67.73
 5000.57   67.15 5006.15   67.84 5009.64   70.59  5018.6   70.92  5038.6   73.63
  5048.6   76.93  5058.6   79.31  5068.6   80.81  5078.6   81.25  5088.6   81.24
    5121   84.37    5221   85.78  5507.4   86.54  5577.4   84.97  5702.7   85.69
#Mann= 4 ,-1 , 0
  4508.1      .1       0  4938.1     .04       0  5068.6     .08       0
  5507.4      .1       0
Bank Sta=4938.1,5068.6
XS Rating Curve= 0
Exp/Cntr=.3,.1

Type RM Length L Ch R = 1 ,523.6   ,180,172,139
BEGIN DESCRIPTION:
Cross Section K111-03-00-X1
END DESCRIPTION:
XS GIS Cut Line= 4
      3119181.44     13933919.58      3119435.62     13934046.88
      3119826.38     13934062.87      3120172.74     13933871.04
#Sta/Elev= 30
  4528.5      84  4568.5      83  4648.5    82.8  4678.5    81.9  4718.5    82.5
  4768.5    82.1  4778.5      83  4812.8    81.9  4817.4   80.66  4880.7   80.33
  4915.2   78.27  4957.7    79.6  4979.1   70.97  4992.6   69.04  4994.5   67.44
  4995.1   66.38  4996.8   65.36  5003.4   65.39  5004.7      66  5005.5   67.12
  5006.2   68.83  5032.1   71.53  5063.1   80.46  5139.2   82.34  5311.8   83.49
  5323.9    84.7  5363.9    85.4  5483.9    86.7  5547.8   85.96  5599.8    86.2
#Mann= 5 ,-1 , 0
  4528.5     .04       0  4957.7     .04       0  5063.1     .04       0
  5547.8      .1       0  5599.8     .99       0
Bank Sta=4957.7,5063.1
XS Rating Curve= 0
Exp/Cntr=.7,.5

Type RM Length L Ch R = 1 ,351.6   ,21,21,21
BEGIN DESCRIPTION:
Upstream Section of Bridge/Culvert/Weir
END DESCRIPTION:
XS GIS Cut Line= 4
       3119180.7     13933934.54      3119569.05     13934236.53
      3119733.95     13934209.64      3120090.12     13933955.86
#Sta/Elev= 30
  4423.2   83.99  4503.2   82.39  4513.2   82.49  4543.2   81.39  4563.2   82.19
  4653.2   81.79  4663.2   82.09  4693.2   81.39  4713.2   82.09  4753.2   80.89
  4793.2   80.79    4921   78.83  4959.1   77.61  4987.5   68.24  4989.1   67.65
  4990.7   67.39  5010.2   67.48  5020.4   70.89    5079   77.35  5080.7   77.67
  5100.7    81.4  5151.2   81.77  5200.3   82.62  5257.5   83.11  5282.2   84.19
  5322.2   83.99  5462.2   85.99  5492.2   85.59  5512.2   86.39  5519.6   86.19
#Mann= 4 ,-1 , 0
  4423.2     .99       0    4921     .04       0  4959.1     .04       0
  5080.7     .99       0
#XS Ineff= 2 , 0
       0  4949.1   78.69    5089       0   77.46
Permanent Ineff=
       F       F
Bank Sta=4959.1,5079
XS Rating Curve= 0
Exp/Cntr=.7,.5

Type RM Length L Ch R = 5 ,341.1   ,,,
BEGIN DESCRIPTION:
325' US TURKEY CREEK
Structure ID: K111-03-00-S1
END DESCRIPTION:
IW Pilot Flow=0
#Inline Weir SE= 30
  4423.2    84.1  4513.2    82.6  4543.2    81.5  4563.2    82.3  4663.2    82.2
  4693.2    81.5  4713.2    82.2  4753.2      81  4793.2    80.9    4921   78.95
  4979.9   78.88 4980.01   76.07  4989.2   76.07 4989.31   72.79  4995.4   72.78
 4995.51   67.52  5004.9   67.57    5005   71.65    5011    71.5  5011.1   74.75
  5020.3   74.96  5020.5   77.94    5079   77.46  5100.7   81.51  5257.5   83.22
  5282.2    84.3  5322.2    84.1  5462.2    86.1  5492.2    85.7  5519.6    86.3
IW Dist,WD,Coef,Skew,MaxSub,Min_El,Is_Ogee,SpillHt,DesHd
10,1,3,0,.95,, 0 ,,,0,0,

Type RM Length L Ch R = 1 ,330.6   ,25,37.7,37.7
BEGIN DESCRIPTION:
Cross Section FIELD_DS
Located At: 325' US TURKEY CREEK
END DESCRIPTION:
XS GIS Cut Line= 6
      3119158.46      13933928.2       3119200.3      13933960.1
      3119586.41     13934254.84       3119754.3     13934226.76
      3120091.79      13933987.8      3120127.65      13933962.3
#Sta/Elev= 30
  4423.2   83.99  4503.2   82.39  4513.2   82.49  4543.2   81.39  4563.2   82.19
  4653.2   81.79  4663.2   82.09  4720.7   80.46  4750.7   79.74  4850.7   79.34
  4870.7    78.6  4900.7   76.26  4920.7   73.72    4933   71.33    4943   70.75
  4986.5   61.04  5000.4   61.02  5014.7   61.03    5083   77.16    5093    79.4
  5103.2   80.53  5113.2   81.22  5143.2   82.02  5163.2   82.95  5303.2   83.58
  5335.6   82.92  5462.2   85.99  5492.2   85.59  5512.2   86.39  5519.6   86.19
#Mann= 4 ,-1 , 0
  4423.2     .99       0  4720.7     .04       0  4870.7     .02       0
    5083     .04       0
Bank Sta=4943,5083
XS Rating Curve= 0
Exp/Cntr=.7,.5

Type RM Length L Ch R = 1 ,292.9   ,0,0,0
BEGIN DESCRIPTION:
K111-03-00-S1 DS_FIELD - DAM DS - XS 1
END DESCRIPTION:
XS GIS Cut Line= 4
      3119418.95     13934169.92      3119593.56     13934290.59
      3119761.45     13934262.51      3119990.94     13934225.93
#Sta/Elev= 30
  4720.7   80.46  4740.7    80.1  4750.7   79.74  4780.7   79.49  4800.7   79.72
  4850.7   79.34  4870.7    78.6  4900.7   76.26  4910.7   75.14  4920.7   73.72
  4930.7   71.93    4933   71.33    4943   70.75  4960.3   66.81  4982.2   61.18
  4986.5   60.41  5000.4   60.39  5014.7    60.4  5045.5   68.28    5083   77.16
    5093    79.4  5103.2   80.53  5113.2   81.22  5143.2   82.02  5153.2   82.65
  5163.2   82.95  5233.2   83.22  5243.2   83.54  5303.2   83.58  5335.6   82.92
#Mann= 3 ,-1 , 0
  4720.7     .04       0  4870.7     .02       0    5083     .04       0
Bank Sta=4943,5083
XS Rating Curve= 0
Exp/Cntr=.3,.1

Chan Stop Cuts=-1